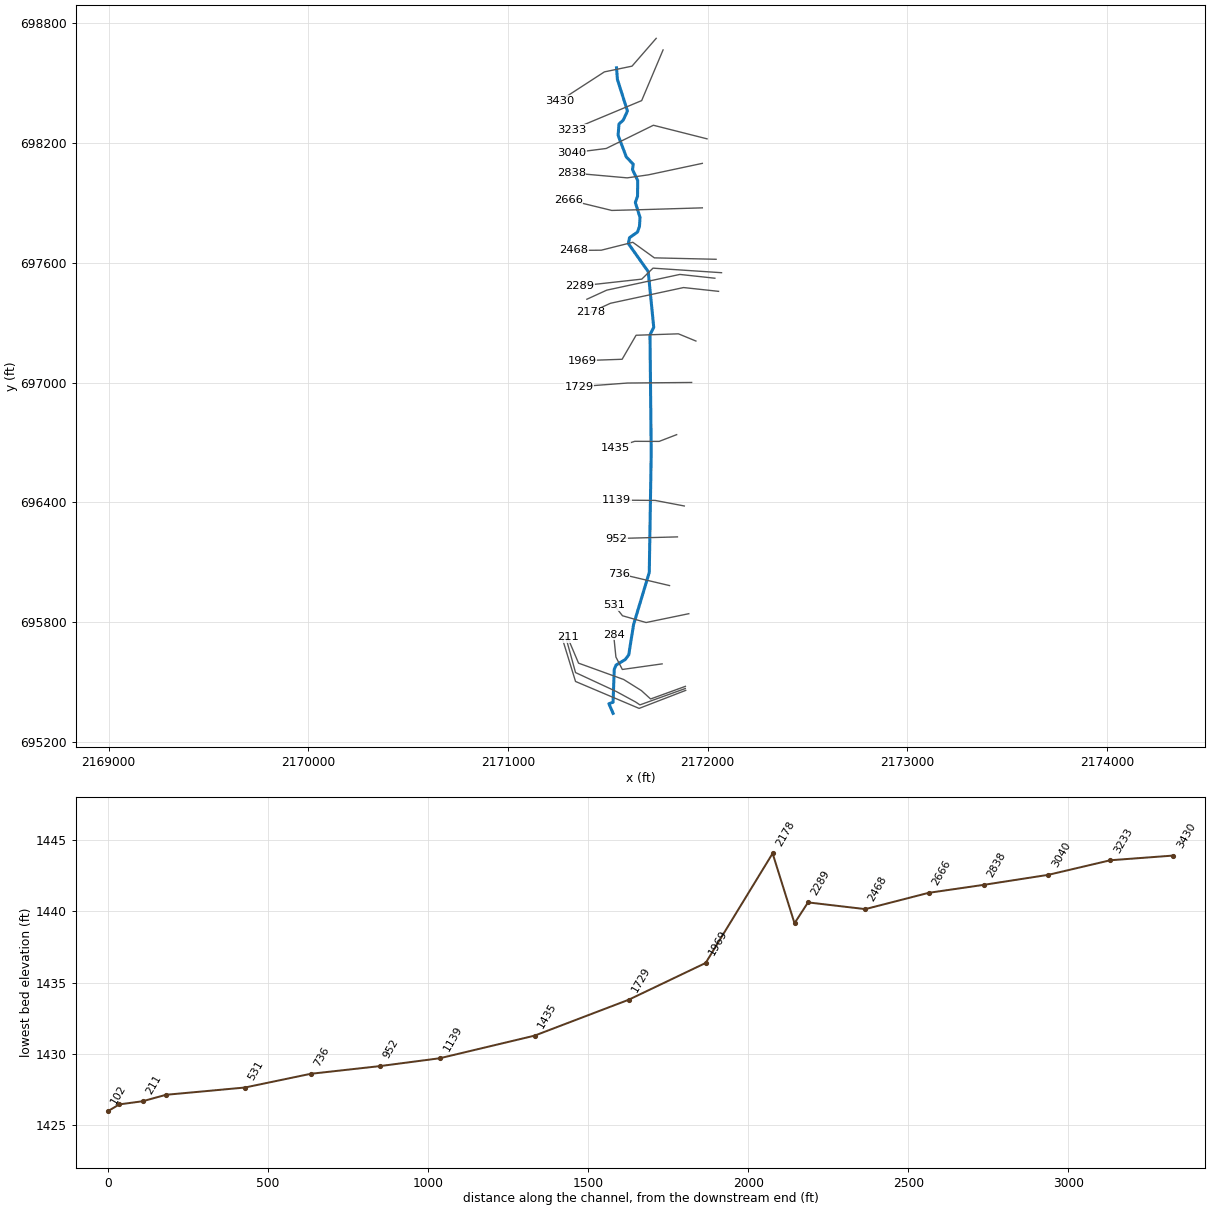
--- BLACKLKRN.prj (project) ---

Proj Title=BLACKLKRN
Current Plan=p01
Default Exp/Contr=0,0
English Units
Geom File=g01
Flow File=f01
Plan File=p01
BEGIN DESCRIPTION:
---------- MODELED AS PART OF WVEMD CTP PROGRAM, 2023----------
Stream Name: Black Lick Run
Flood Zone:  AFH
Upshur County, WV
HEC-RAS Version: RAS 6.3
Vertical Datum: NAVD88
Projection: NAD 1983 StatePlane West Virginia S FIPS 4702 (US Feet)
Terrain: 1-meter LIDAR (FEMA Region III 3DEP collected 2016-2018)
Land Use: 2019 NLCD
Hydrologic Method:
WV SIR2010-5033 regression equations
Additional Model Notes:
Normal depth tie in to Bull Run
END DESCRIPTION:
DSS Export Rating Curves= 0
DSS Export Rating Curve Sorted= 0
DSS Export Volume Flow Curves= 0
DXF OffsetX= 0
DXF OffsetY= 0
DXF ScaleX= 0
DXF ScaleY= 0

--- BLACKLKRN.p01 (plan) ---

Plan Title=Floodplain
Program Version=6.31
Short Identifier=Floodplain
Geom File=g01
Flow File=f01
Subcritical Flow
K Sum by GR= 0
Std Step Tol= 0.01
Critical Tol= 0.01
Num of Std Step Trials= 20
Max Error Tol= 0.3
Flow Tol Ratio= 0.001
Split Flow NTrial= 30
Split Flow Tol= 0.02
Split Flow Ratio= 0.02
Log Output Level= 0
Friction Slope Method= 1
Unsteady Friction Slope Method= 2
Unsteady Bridges Friction Slope Method= 1
Parabolic Critical Depth
Global Vel Dist= 0 , 0 , 0
Global Log Level= 0
CheckData=True
Encroach Param=-1 ,0,0, 0
Mapping Interval=1HOUR
Computation Time Step Use Courant=        0
Computation Time Step Use Time Series=    0
Computation Time Step Count To Double=0
Computation Time Step Max Doubling=0
Computation Time Step Max Halving=0
Computation Time Step Residence Courant=0
Run HTab= 0
Run UNet= 0
Run Sediment= 0
Run PostProcess= 0
Run WQNet= 0
Run RASMapper=-1
UNET Theta= 0
UNET Theta Warmup= 0
UNET ZTol= 0
UNET ZSATol= 0
UNET MxIter= 0
UNET Max Iter WO Improvement= 0
UNET MaxInSteps= 0
UNET DtIC= 0
UNET DtMin= 0
UNET MaxCRTS= 0
UNET WFStab= 0
UNET SFStab= 0
UNET WFX= 1
UNET SFX= 1
UNET Gravity=32.17405
UNET 1D Methodology=Finite Difference
UNET DSS MLevel= 1
UNET Pardiso=0
UNET DZMax Abort= 0
UNET Use Existing IB Tables= 0
UNET Froude Reduction=False
UNET Froude Limit= 0
UNET Froude Power= 0
UNET D1 Cores= 0
UNET WindReference=Eulerian
UNET WindDragFormulation=Hsu (1988)
UNET D2 Coriolis=0
UNET D2 Cores= 0
UNET D2 Theta= 1
UNET D2 Theta Warmup= 1
UNET D2 Z Tol= 0.01
UNET D2 Volume Tol= 0.01
UNET D2 Max Iterations= 20
UNET D2 Equation= 0
UNET D2 RampUpFraction=0.1
UNET D2 TimeSlices= 1
UNET D2 Turbulence Formulation=Non-Conservative (original)
UNET D2 Eddy Viscosity=0.3
UNET D2 Transverse Eddy Viscosity=0.1
UNET D2 Smagorinsky Mixing=0
UNET D2 BCVolumeCheck=0
UNET D2 Cores=0
UNET D2 SolverType=PARDISO (Direct)
UNET D2 Minimum Iterations= 3
UNET D2 Maximum Iterations= 30
UNET D2 Restart Number= 10
UNET D2 Relaxation Coeff=1.3
UNET D2 SOR Precondition Iterations= 10
UNET D2 ILUT Maximum Fill= 8
UNET D2 ILUT Tolerance=1E-08
UNET D2 Convergence Tolerance=0.00001
UNET D1D2 MaxIter= 0
UNET D1D2 ZTol=0.01
UNET D1D2 QTol=0.1
UNET D1D2 MinQTol=1
Write IC File= 0
Write IC File at Fixed DateTime=0
Write IC File at Sim End=0
Echo Input=False
Echo Parameters=False
Echo Output=False
Write Detailed= 0
HDF Write Warmup=0
HDF Write Time Slices=0
HDF Flush=0
HDF Compression= 1
HDF Chunk Size= 1
HDF Spatial Parts= 1
HDF Use Max Rows=0
HDF Fixed Rows= 1
Calibration Method= 0
Calibration Iterations= 20
Calibration Max Change=0.05
Calibration Tolerance=0.2
Calibration Maximum=1.5
Calibration Minimum=0.5
Calibration Optimization Method= 1
WQ AD Non Conservative
WQ ULTIMATE=-1
WQ Max Comp Step=1HOUR
WQ Output Interval=15MIN
WQ Output Selected Increments= 0
WQ Create Restart=0
WQ Fixed Restart=0
WQ System Summary=0
WQ Write To DSS=0
Sorting and Armoring Iterations= 10
XS Update Threshold= 0.02
Bed Roughness Predictor= 0
Hydraulics Update Threshold= 0.02
Energy Slope Method= 1
Volume Change Method= 1
Sediment Retention Method= 0
Sediment TS Multiplier= 1
Warm Up Method= 0
XS Weighting Method= 0
Number of US Weighted Cross Sections= 1
Number of DS Weighted Cross Sections= 1
Upstream XS Weight=0
Main XS Weight=1
Downstream XS Weight=0
Number of DS XS's Weighted with US Boundary= 1
Upstream Boundary Weight= 1
Weight of XSs Associated with US Boundary= 0
Number of US XS's Weighted with DS Boundary= 1
Downstream Boundary Weight= 0.5
Weight of XSs Associated with DS Boundary= 0.5
Percentile Method= 0
Sediment Output Level= 3
Mass or Volume Output= 0
Output Increment Type= 1
Profile and TS Output Increment= 1
Transport Output Increment 1
XS Output Flag= 0
XS Output Increment= 10
Read HDF5 Sediment Hotstart= 0
Sediment Hotstart Type= 0
Write Gradation File= 0
Read Gradation Hotstart= 0
Write HDF5 File= 1
Write Binary Output= 1
Write DSS Sediment File= 0
DSS Sediment Output Type= 1
SV Curve= 0
Specific Gage Flag= 0
Subcell Erosion Methods= 0
Subcell Deposition Methods= 0
Advection Scheme= 1
Matrix Solver= 0
Implicit Weighting Factor= 1
Maximum Outer Loop Convergence Iterations= 5
Convergence Maximum Absolute= 0.001
Convergence RMSE= 0.0001
Grain Fractions Max Abs Error= 0.001
Max Subgrid Regions= 1
Max Subgrid Length Scale= 3.402823E+38
Initial Layer Thickness= 3.402823E+38
Min Layer Thickness= 3.402823E+38
Max Layer Thickness= 3.402823E+38
Number of Layers= 5

--- BLACKLKRN.f01 (steady flow) ---

Flow Title=Flows
Program Version=6.31
Number of Profiles= 1
Profile Names=01pct
River Rch & RM=BLACKLKRN,Main            ,3430
     358
Boundary for River Rch & Prof#=BLACKLKRN,Main            , 1
Up Type= 0
Dn Type= 3
Dn Slope=0.00159
DSS Import GetInterval= 0
DSS Import GetPeak= 0
DSS Import FillOption= 0

--- BLACKLKRN.g01 (geometry) ---

Geom Title=Geometry
Program Version=6.31

River Reach=BLACKLKRN       ,Main
Reach XY= 30
2171543.54494618698577.1177399712171548.01529886698518.937651485
2171598.28267699698360.8012497742171577.01627612698314.800490499
2171555.86275708698295.6147406692171551.43527635698239.533318087
     2171592.305      698131.202     2171627.446      698093.772
     2171623.439      698067.788     2171649.709      698012.673
2171648.78365044697933.8502062182171637.66624633697902.649749513
      2171661.27      697827.868     2171658.437      697783.484
     2171648.736       697754.61     2171608.587       697726.28
     2171602.835      697696.691      2171702.22      697556.556
2171729.87061799697277.613909881     2171711.177      697239.601
     2171717.301       696649.562171707.54605338696049.804526691
     2171628.962       695788.75     2171604.724      695636.883
     2171587.354      695613.532     2171541.511      695585.946
      2171532.21      695564.5692171526.18708958695399.684602559
 2171505.3539872695392.010423034     2171526.458      695343.823

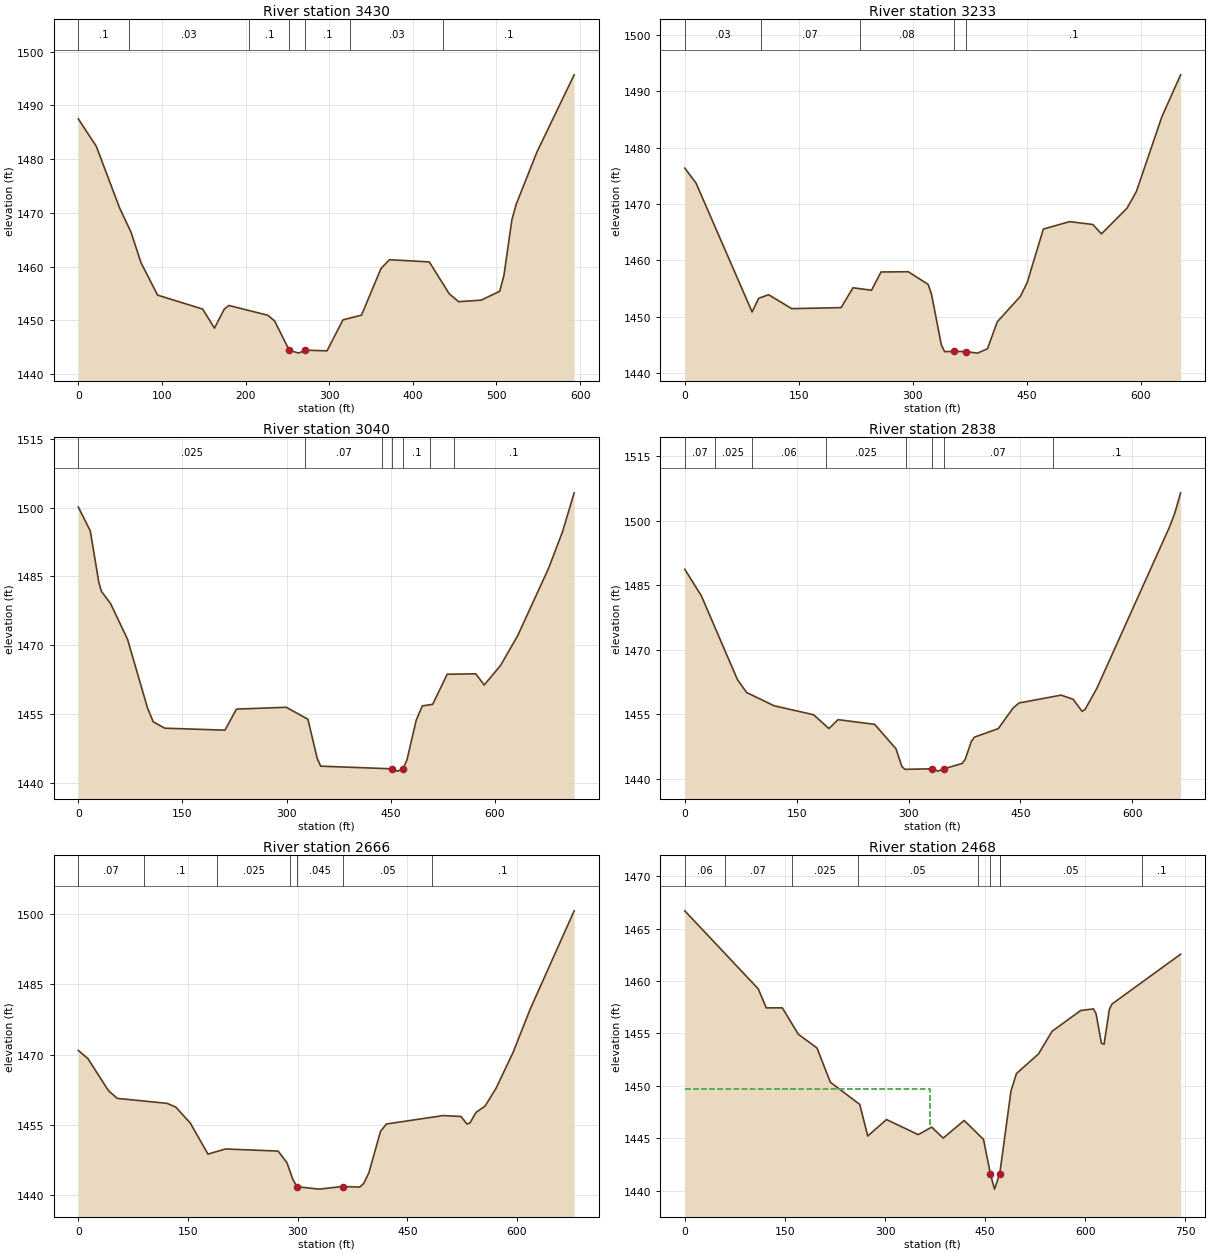
Type RM Length L Ch R = 1 ,3430    ,197.2,197.2,197.2
XS GIS Cut Line= 4
2171742.30674462698724.7717215362171621.15867359698585.426227868
2171482.91454012698556.8260287842171258.83316495698411.410337945
#Sta/Elev= 30
       0  1487.5    21.5 1482.39    49.4  1470.9    63.1 1466.37    74.9 1460.74
    94.8 1454.69   148.7 1452.09   162.8 1448.54   174.4 1452.06     180 1452.76
   226.5 1450.95   234.7 1449.88  252.17 1444.45   263.3 1443.89   271.4 1444.44
   297.4 1444.32   316.4 1450.08   338.6 1450.96   361.9 1459.64     372 1461.28
   419.7 1460.87   443.5 1454.94   454.8 1453.47   481.7 1453.75   503.9 1455.41
   508.9 1458.34   518.4 1468.68   523.6  1471.6   548.4 1481.33   592.9  1495.7
#Mann= 7 ,-1,0
       0      .1       0      60     .03       0  204.65      .1       0
  252.17    .045       0   271.4      .1       0  324.65     .03       0
  435.82      .1       0
Bank Sta=252.17,271.4
XS Rating Curve= 0 ,0
Exp/Cntr=0.3,0.1

Type RM Length L Ch R = 1 ,3233    ,189.9,193.6,192.1
XS GIS Cut Line= 3
 2171776.7107539698666.7825398662171669.45976611698412.931466399
2171321.44462746698267.527086993
#Sta/Elev= 30
       0 1476.37    14.8 1473.71    88.6 1450.86    97.3 1453.28   110.3 1453.92
   140.7 1451.45   205.8 1451.63   221.4 1455.15   245.8 1454.71   258.3 1457.95
   294.3 1457.99   320.3 1455.75   324.7 1454.05   337.7 1445.03     342 1443.83
     355 1443.86  370.09 1443.84   385.3 1443.56   398.4 1444.33   411.4 1449.12
   441.7 1453.62   450.7 1456.06     472 1465.56   506.7 1466.88   537.1 1466.37
   548.5 1464.71   582.1 1469.26   594.4 1472.19   628.1  1485.5   652.7 1492.91
#Mann= 5 ,-1,0
       0     .03       0     100     .07       0     230     .08       0
     355    .045       0  370.09      .1       0
Bank Sta=355,370.09
XS Rating Curve= 0 ,0
Exp/Cntr(USF)=0,0
Exp/Cntr=0.3,0.1

Type RM Length L Ch R = 1 ,3040    ,203.7,201.4,195.3
XS GIS Cut Line= 4
2171996.89487893698221.419188167 2171728.1886772698289.436834055
2171491.80817973698173.0885485242171319.61413911698151.184049206
#Sta/Elev= 30
       0  1500.1    17.2 1494.91    29.6 1483.65    33.3 1481.72    46.5 1479.04
    70.9 1471.27    99.8 1456.23     108 1453.28   124.5  1451.9   211.2 1451.47
   227.8 1456.06   299.5 1456.46   330.7 1453.85   344.1 1445.32   349.1 1443.62
   451.1 1443.05     460 1442.54  467.73 1443.07   473.4 1444.99   486.7 1453.65
   495.5 1456.76   510.4  1457.1   531.3 1463.66   572.5 1463.75   584.6 1461.31
   608.2 1465.57     633 1472.11   677.4 1486.77   697.4 1494.69   714.2  1503.2
#Mann= 7 ,-1,0
       0    .025       0  327.18     .07       0  437.18      .1       0
   451.1    .045       0  467.73      .1       0  507.18     .08       0
  540.64      .1       0
Bank Sta=451.1,467.73
XS Rating Curve= 0 ,0
Exp/Cntr=0.3,0.1

Type RM Length L Ch R = 1 ,2838    ,171.2,172.2,171.6
XS GIS Cut Line= 4
2171973.22683171698098.5393111692171702.99089407698041.064794664
2171596.88152447698025.9475694812171316.56016436698050.886381584
#Sta/Elev= 30
       0 1488.73    22.3 1482.53    70.6  1463.1    82.9  1460.1   119.7 1457.03
   172.8 1454.93   193.3 1451.73   205.5  1453.8   254.6 1452.71   283.2 1447.04
   291.2 1442.88   295.3 1442.26   331.6 1442.38   339.7 1441.84  347.32 1442.37
   372.1 1443.63   376.1 1444.61   384.2 1448.72   388.2 1449.72   420.4 1451.72
   440.4 1456.54   448.4 1457.68   504.6 1459.49   520.7 1458.54   532.8 1455.72
   536.8 1456.19   552.6 1461.09   649.6 1498.39   657.2 1501.84   664.9 1506.49
#Mann= 8 ,-1,0
       0     .07       0      40    .025       0      90     .06       0
     190    .025       0  296.28     .07       0   331.6    .045       0
  347.32     .07       0  493.46      .1       0
Bank Sta=331.6,347.32
XS Rating Curve= 0 ,0
Exp/Cntr=0.3,0.1

Type RM Length L Ch R = 1 ,2666    ,200.4,198,188.5
XS GIS Cut Line= 4
2171973.35162891697875.7574133092171677.93218271697866.915109984
2171519.63846723697862.7987148822171301.84302516697915.870245023
#Sta/Elev= 30
       0 1470.87    13.2 1469.11    41.2 1462.29    53.2 1460.64   121.2 1459.58
   133.2  1458.8   153.2 1455.36   177.3 1448.75   201.3 1449.85   273.3 1449.39
   285.3 1446.92   293.3 1443.39   298.9  1441.8   329.3 1441.28   361.3 1441.84
   384.8 1441.72   390.1 1442.45   397.3 1444.74   413.3 1453.61   421.4 1455.18
   498.9 1456.97   523.3 1456.78   531.6 1455.16   535.7 1455.43   543.9 1457.65
   556.3    1459   571.3  1462.8   594.5 1470.42     618 1479.69   678.1 1500.65
#Mann= 7 ,-1,0
       0     .07       0      90      .1       0     190    .025       0
     290     .05       0   298.9    .045       0   361.3     .05       0
   483.9      .1       0
Bank Sta=298.9,361.3
XS Rating Curve= 0 ,0
Exp/Cntr=0.3,0.1

Type RM Length L Ch R = 1 ,2468    ,171.1,178.8,185.3
XS GIS Cut Line= 5
 2172042.1988503697618.1470342732171732.98280404 697625.34359808
2171625.11402251 697703.261539132171467.22115733697663.666594158
2171329.51897357697662.552021481
#Sta/Elev= 30
       0  1466.7   110.1 1459.25   122.1 1457.44   146.1 1457.44   170.1 1454.92
   198.1 1453.61   218.1 1450.34   262.1 1448.23   274.1 1445.21   302.2 1446.78
   349.8 1445.34   369.9 1446.06   387.1 1445.01   418.6 1446.69   447.5 1444.89
     458 1441.58     464 1440.14  471.85 1441.59   488.7 1449.49   496.9 1451.17
   529.9 1453.04   550.4 1455.21   593.2 1457.19   612.2 1457.34   616.2 1456.89
   624.2 1454.06   628.2 1453.97   636.2 1457.31   640.2 1457.81   742.9 1462.56
#Mann= 9 ,-1,0
       0     .06       0      60     .07       0     160    .025       0
     260     .05       0   439.3    .025       0     458    .045       0
  471.85    .025       0  472.37     .05       0  685.15      .1       0
#XS Ineff= 2 , 0
          367.77 1449.69
Permanent Ineff=
       F       F
Bank Sta=458,471.85
XS Rating Curve= 0 ,0
Exp/Cntr=0.3,0.1

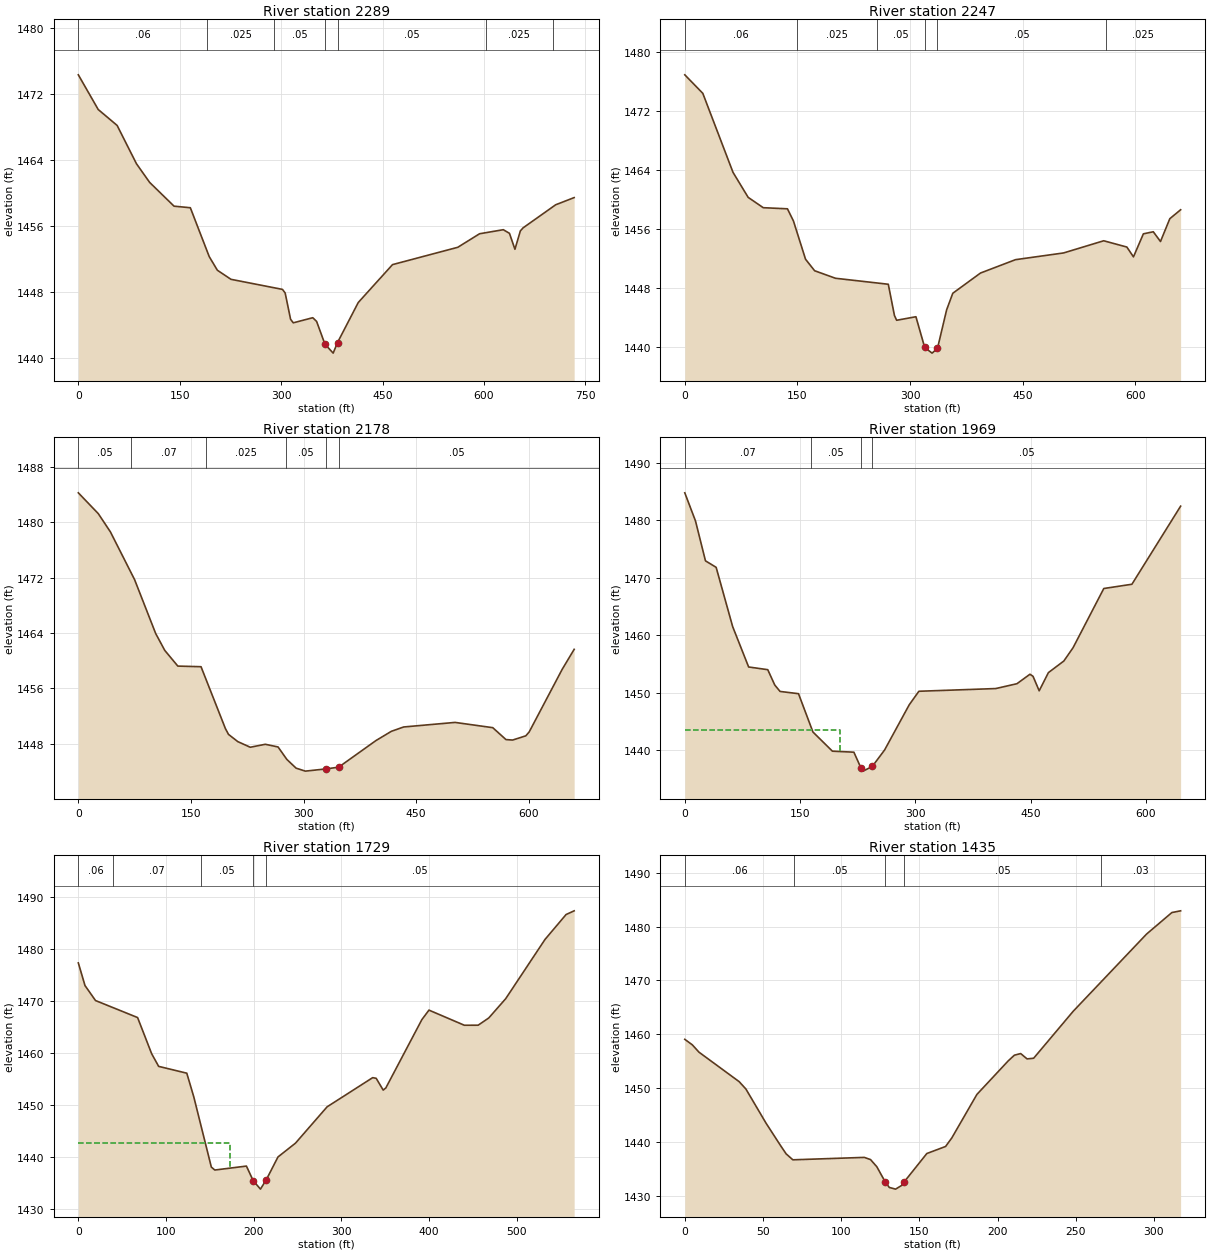
Type RM Length L Ch R = 1 ,2289    ,51,42.2,35
XS GIS Cut Line= 4
2172069.46670348697550.9132653382171726.17062707697573.730527214
2171670.16462065697518.7616690582171361.09443706697484.535776245
#Sta/Elev= 30
       0 1474.32    29.4 1470.12    57.4 1468.19      86 1463.55   105.5 1461.29
   141.6 1458.41   165.7 1458.22   193.7 1452.29   205.7 1450.65   225.8 1449.55
     302 1448.33     306 1447.89     314 1444.71     318 1444.28   346.8  1444.9
   352.5 1444.45   364.8  1441.7     377 1440.61   383.41441.887   414.1 1446.74
   464.8 1451.33   561.4 1453.43   593.6 1455.07   628.7 1455.56   637.8 1455.12
   645.9 1453.19   653.9 1455.41   657.9 1455.78   706.2 1458.58   733.5 1459.45
#Mann= 7 ,-1,0
       0     .06       0     190    .025       0     290     .05       0
   364.8    .045       0   383.4     .05       0  602.53    .025       0
  702.53     .05       0
Bank Sta=364.8,383.4
XS Rating Curve= 0 ,0
Exp/Cntr(USF)=0,0
Exp/Cntr=0.3,0.1

Type RM Length L Ch R = 1 ,2247    ,68.5,68.4,68.4
XS GIS Cut Line= 4
2172036.04518128697523.3131269082171860.71980078697542.289398582
2171494.59433171697463.5493203922171395.00533487697418.022921837
#Sta/Elev= 30
       0 1476.85      24 1474.34    64.2 1463.64    84.4 1460.25   104.5 1458.85
   136.7  1458.7   144.7 1457.05   160.8 1451.87   172.9 1450.31   200.7 1449.29
     271 1448.48   279.2 1444.25   282.1  1443.6   307.8 1444.08   319.51439.915
   329.3 1439.15   336.5 1439.79   348.7 1445.02   356.9 1447.26   393.8    1450
   440.4 1451.81   504.4 1452.72   557.9 1454.37   588.7 1453.52   597.5 1452.19
   610.7 1455.31   623.9 1455.59   633.5 1454.27   645.9 1457.36   660.3 1458.57
#Mann= 6 ,-1,0
       0     .06       0     150    .025       0  256.35     .05       0
   319.5    .045       0   336.5     .05       0  560.85    .025       0
Bank Sta=319.5,336.5
XS Rating Curve= 0 ,0
Exp/Cntr(USF)=0,0
Exp/Cntr=0.3,0.1

Type RM Length L Ch R = 1 ,2178    ,210.5,209.1,206.2
XS GIS Cut Line= 4
2172054.61313958697457.5761923692171879.28775908697476.552464043
2171513.16229001697397.8123858532171413.57329317697352.285987298
#Sta/Elev= 30
       0 1484.26    26.6 1481.25    42.7 1478.62    74.9 1471.72     103 1463.93
   115.1 1461.49   132.5 1459.22   163.4 1459.13   195.9 1450.18     200 1449.35
   212.3 1448.31     229 1447.49     249 1447.92     266 1447.53   277.7 1445.73
     290 1444.47   302.3 1444.04     3301444.361   346.71444.613   396.4 1448.46
   416.8 1449.79   433.2 1450.42   501.7 1451.08   551.9 1450.32   569.5  1448.6
   578.3 1448.53   595.9 1449.14   600.4  1449.7   644.3 1458.74   660.3 1461.64
#Mann= 6 ,-1,0
       0     .05       0      70     .07       0     170    .025       0
  276.35     .05       0     330    .045       0   346.7     .05       0
Bank Sta=330,346.7
XS Rating Curve= 0 ,0
Exp/Cntr(USF)=0,0
Exp/Cntr=0.3,0.1

Type RM Length L Ch R = 1 ,1969    ,241.1,240.9,240.5
XS GIS Cut Line= 5
2171941.04851307697208.7687878012171853.44852194697244.811876107
2171641.50410227697237.6537352052171571.56540468697117.359175366
2171372.18905041697110.397929293
#Sta/Elev= 30
       0 1484.74    13.9 1479.86    26.9 1472.92    40.8 1471.79    62.3 1461.49
    83.1 1454.47     108    1454   117.1 1451.34     124 1450.22     148 1449.83
   166.8 1443.17   192.1 1439.84   220.1 1439.66   229.31436.912   232.1 1436.37
   244.1 1437.19   260.1 1440.05   292.1 1447.89   304.7 1450.25   404.7 1450.72
   432.3 1451.56   449.3 1453.21   453.3 1452.85   461.3 1450.33   473.3 1453.49
   493.4 1455.51   505.4 1457.82   545.4 1468.11     582 1468.85   645.4 1482.42
#Mann= 4 ,-1,0
       0     .07       0  164.73     .05       0   229.3    .045       0
   244.1     .05       0
#XS Ineff= 2 , 0
          201.52 1443.49
Permanent Ineff=
       F       F
Bank Sta=229.3,244.1
XS Rating Curve= 0 ,0
Exp/Cntr=0.3,0.1

Type RM Length L Ch R = 1 ,1729    ,293.7,293.6,293.4
XS GIS Cut Line= 3
2171919.82108891 697001.232957072171598.64436429696998.382997229
2171355.06818747696980.097548989
#Sta/Elev= 30
       0 1477.26     7.6 1472.91    19.6 1470.03    67.6 1466.76    83.6 1459.82
    91.6 1457.38   123.7 1456.07   131.7 1451.51   151.7 1438.02   155.7 1437.46
   191.7 1438.22   199.41435.429   207.7 1433.79   214.4  1435.6   227.7 1439.97
   247.7 1442.63   283.7  1449.6   335.7 1455.21   339.7 1455.09   347.7 1452.82
   350.7 1453.23   391.8 1466.36   399.9 1468.19   440.3 1465.28     456 1465.29
   468.1 1466.68   487.4 1470.38   532.3 1481.78   556.3 1486.56   565.5 1487.27
#Mann= 5 ,-1,0
       0     .06       0      40     .07       0     140     .05       0
   199.4    .045       0   214.4     .05       0
#XS Ineff= 2 , 0
          173.41 1442.59
Permanent Ineff=
       F       F
Bank Sta=199.4,214.4
XS Rating Curve= 0 ,0
Exp/Cntr=0.3,0.1

Type RM Length L Ch R = 1 ,1435    ,295.7,295.7,295.6
XS GIS Cut Line= 4
2171844.66905661696739.774496817 2171756.9246368696705.989040404
 2171634.6656836696706.3934300582171538.87905844 696674.94934531
#Sta/Elev= 30
       0 1459.08     4.8 1458.06     9.1 1456.69    34.8 1451.22    39.1 1449.85
    51.9 1443.55    61.2 1439.38    64.8 1437.83    69.1 1436.72   114.8 1437.17
   118.8 1436.76   122.8 1435.44   128.2 1432.61   130.8 1431.59   134.8 1431.28
   138.8 1431.98   140.31432.624   154.8 1437.89   166.8  1439.2   170.8  1440.8
   186.8 1448.85   206.8 1455.07   210.8 1456.14   214.8 1456.44   218.9 1455.45
   223.1 1455.57   248.4 1464.29   295.3 1478.61   311.5 1482.61   317.1 1482.93
#Mann= 5 ,-1,0
       0     .06       0      70     .05       0   128.2    .045       0
   140.3     .05       0  266.28     .03       0
Bank Sta=128.2,140.3
XS Rating Curve= 0 ,0
Exp/Cntr=0.3,0.1

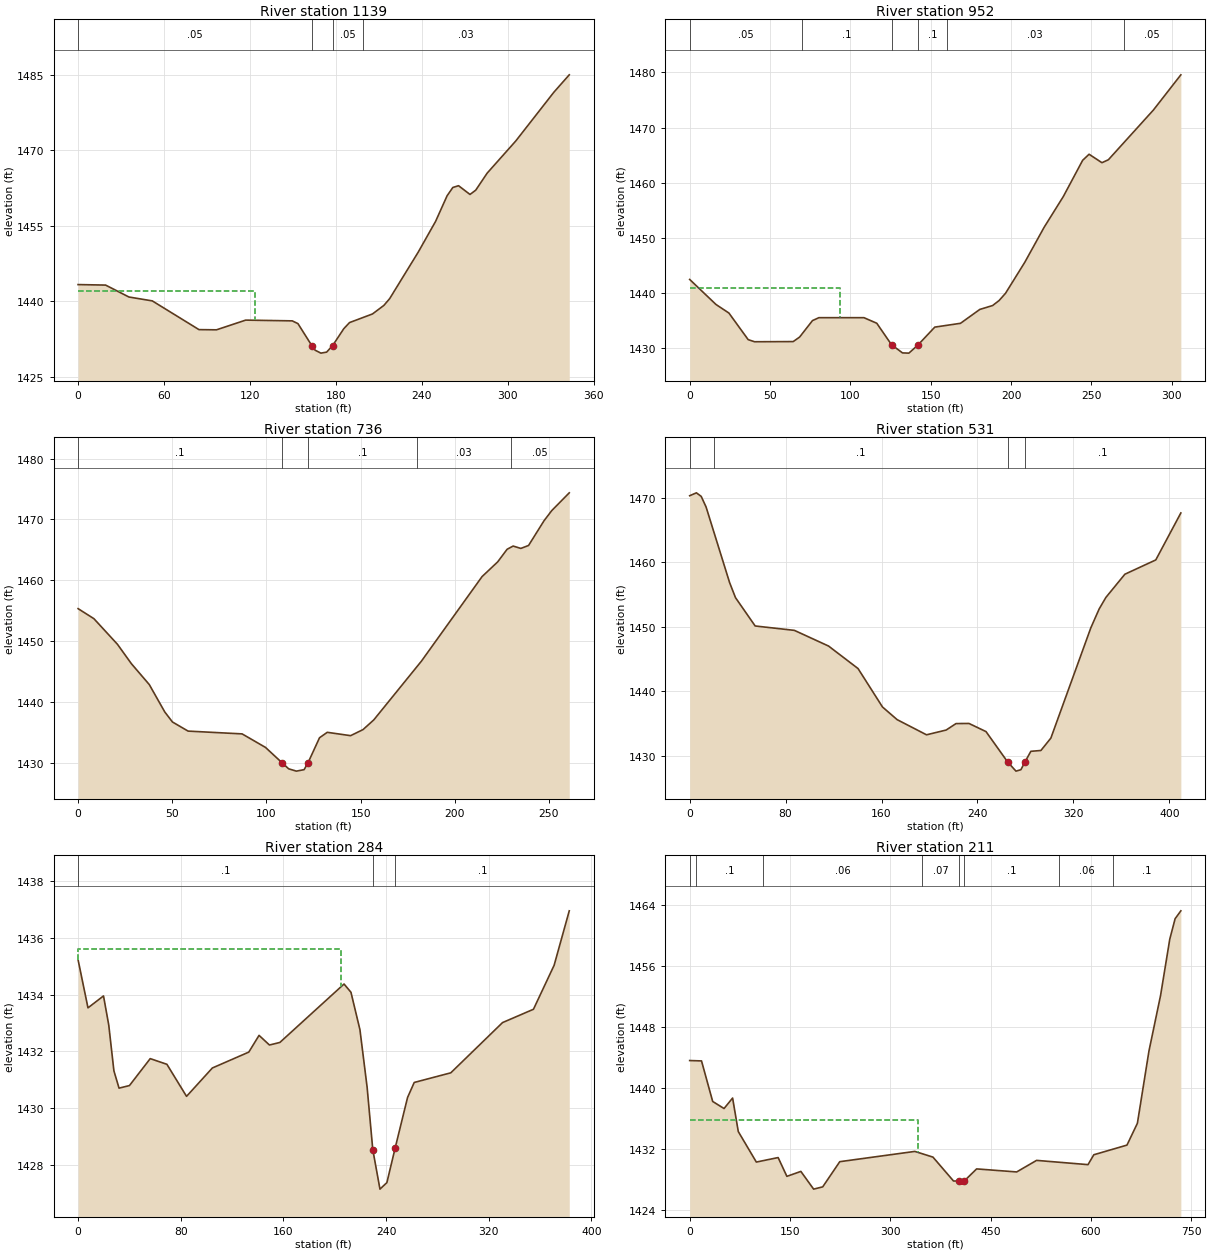
Type RM Length L Ch R = 1 ,1139    ,186.5,187,187.4
XS GIS Cut Line= 3
2171883.08195539696382.5345381552171736.84188214696410.449156999
2171542.77894506696411.913148052
#Sta/Elev= 30
       0 1443.32    19.2 1443.22    35.5 1440.85    51.8 1440.08    84.4 1434.37
    96.6 1434.33     117 1436.26   149.5 1436.11   153.5 1435.56   163.21431.177
   165.5 1430.28   169.5  1429.7   173.5  1429.9   177.71431.203   185.5 1434.56
   189.5 1435.77   205.5 1437.48   213.5 1439.19   217.5 1440.52   237.5 1449.79
   249.6 1455.89   257.6 1460.96   261.6 1462.61   265.6 1462.97   273.6 1461.23
   277.6 1462.08   285.6 1465.47   305.6 1471.87   332.2 1481.56   342.9    1485
#Mann= 4 ,-1,0
       0     .05       0   163.2    .045       0   177.7     .05       0
  198.88     .03       0
#XS Ineff= 2 , 0
          123.24 1442.07
Permanent Ineff=
       F       F
Bank Sta=163.2,177.7
XS Rating Curve= 0 ,0
Exp/Cntr=0.3,0.1

Type RM Length L Ch R = 1 ,952     ,219.4,216.3,213.1
XS GIS Cut Line= 2
2171848.57191349696227.7545989132171543.09875635696219.526365724
#Sta/Elev= 30
       0 1442.49    16.4 1437.95    24.4 1436.41    36.4 1431.59    40.4 1431.21
    64.4 1431.24    68.4 1432.06    76.4 1435.04    80.4 1435.57   108.4 1435.57
   116.4 1434.56   125.61430.667   132.4 1429.19   136.4 1429.15     1421430.616
   152.5 1433.86   168.5 1434.55   180.5 1437.06   188.5 1437.77   192.5 1438.67
   196.5 1439.98   208.5  1445.6   220.5 1451.92   232.5 1457.52   244.5 1464.06
   248.5 1465.16   256.5 1463.63   260.5 1464.16   288.5 1473.16   305.6 1479.54
#Mann= 6 ,-1,0
       0     .05       0      70      .1       0   125.6    .045       0
     142      .1       0     160     .03       0     270     .05       0
#XS Ineff= 2 , 0
           93.46 1440.86
Permanent Ineff=
       F       F
Bank Sta=125.6,142
XS Rating Curve= 0 ,0
Exp/Cntr(USF)=0,0
Exp/Cntr=0.3,0.1

Type RM Length L Ch R = 1 ,736     ,205.7,205.4,204.7
XS GIS Cut Line= 2
2171808.97497316695983.8945425692171555.14634545696043.843251082
#Sta/Elev= 30
       0 1455.32     8.4 1453.67    20.9 1449.46    28.3 1446.27    37.8 1442.84
      46 1438.35    50.1 1436.69    58.4 1435.19    87.1 1434.73    99.5 1432.51
   108.31429.985   111.8 1428.99   115.9 1428.61     120 1428.85   122.11429.992
   128.2  1434.1   132.3 1434.99   144.7 1434.44   151.3 1435.44     157 1437.03
   182.3 1446.69   214.5 1460.59   222.8 1463.01   227.8 1465.08     231 1465.61
   235.1 1465.22   239.2 1465.71   247.4 1469.77   251.5 1471.44   260.8 1474.36
#Mann= 5 ,-1,0
       0      .1       0   108.3    .045       0   122.1      .1       0
     180     .03       0     230     .05       0
Bank Sta=108.3,122.1
XS Rating Curve= 0 ,0
Exp/Cntr=0.3,0.1

Type RM Length L Ch R = 1 ,531     ,257.5,246.7,236.1
XS GIS Cut Line= 4
2171905.62389239695843.0846973252171691.68982947695798.857943934
2171573.40897738695832.7994058392171531.23928229695886.282921568
#Sta/Elev= 30
       0 1470.34     5.6 1470.79     9.6 1470.24    13.7 1468.58    33.3 1456.87
    38.2 1454.54    54.6 1450.15    87.3 1449.47   115.8 1447.04   140.4 1443.55
   160.8 1437.59     173 1435.63   197.5 1433.28   213.9 1434.02   222.1 1435.02
   232.9 1435.04   247.1 1433.78   265.2 1429.06   272.1 1427.65   276.2 1427.87
  279.54 1429.05   284.5 1430.72   292.9 1430.85   301.2 1432.77   334.5 1449.85
   341.5  1452.8   347.1 1454.58   362.9 1458.17   388.7 1460.39   409.6 1467.67
#Mann= 4 ,-1,0
       0     .06       0      20      .1       0   265.2    .045       0
  279.54      .1       0
Bank Sta=265.2,279.54
XS Rating Curve= 0 ,0
Exp/Cntr(USF)=0,0
Exp/Cntr=0.3,0.1

Type RM Length L Ch R = 1 ,284     ,64.9,72.5,80.1
XS GIS Cut Line= 4
2171771.80515082695591.7401888222171572.67268354695563.737185611
2171540.52108727695625.9660816362171529.11245633695736.940946214
#Sta/Elev= 30
       0 1435.22     7.7 1433.53    19.8 1433.95    23.9 1432.92    27.9 1431.31
    31.9  1430.7      40 1430.79    56.2 1431.74    69.2 1431.54    84.5 1430.41
   104.6 1431.41     133 1431.97     141 1432.56   149.1 1432.22   157.2 1432.31
   207.2 1434.37   212.6 1434.08   219.6 1432.76   225.2 1430.73   229.61428.534
   235.2 1427.14   240.6 1427.37   247.1  1428.6   256.7 1430.37   261.9  1430.9
   290.4 1431.24   330.7 1433.01   354.8 1433.48   370.9 1435.03   382.7 1436.95
#Mann= 3 ,-1,0
       0      .1       0   229.6    .045       0   247.1      .1       0
#XS Ineff= 2 , 0
          205.07 1435.62
Permanent Ineff=
       F       F
Bank Sta=229.6,247.1
XS Rating Curve= 0 ,0
Exp/Cntr(USF)=0,0
Exp/Cntr=0.3,0.1

Type RM Length L Ch R = 1 ,211     ,74.2,72.8,73.4
XS GIS Cut Line= 6
2171888.48433087695479.209601844  2171714.243422695415.943557552
2171668.09032412695457.9480623692171579.41414728695513.435494658
2171353.31582506695595.370207757 2171298.3469669695725.013741142
#Sta/Elev= 30
       0  1443.6    17.7 1443.55    34.4 1438.22    51.4 1437.29    64.2 1438.67
    72.7 1434.26    99.7 1430.25   132.3 1430.84   145.4 1428.37   166.3 1429.02
   185.4 1426.69     199 1426.99   224.5  1430.3   336.8 1431.65   363.9  1430.9
   394.6 1427.76   402.31427.742     410  1427.7   429.2 1429.35   489.1 1428.95
   518.9 1430.47   595.8 1429.91   604.5 1431.21   654.1 1432.48   669.7 1435.35
     687 1444.86   704.4 1452.18   718.1 1459.55   726.1 1462.25   734.7 1463.29
#Mann= 8 ,-1,0
       0     .06       0      10      .1       0     110     .06       0
  347.78     .07       0   402.3    .045       0     410      .1       0
  552.98     .06       0  633.84      .1       0
#XS Ineff= 2 , 0
          342.08 1435.76
Permanent Ineff=
       F       F
Bank Sta=402.3,410
XS Rating Curve= 0 ,0
Exp/Cntr(USF)=0,0
Exp/Cntr=0.3,0.1

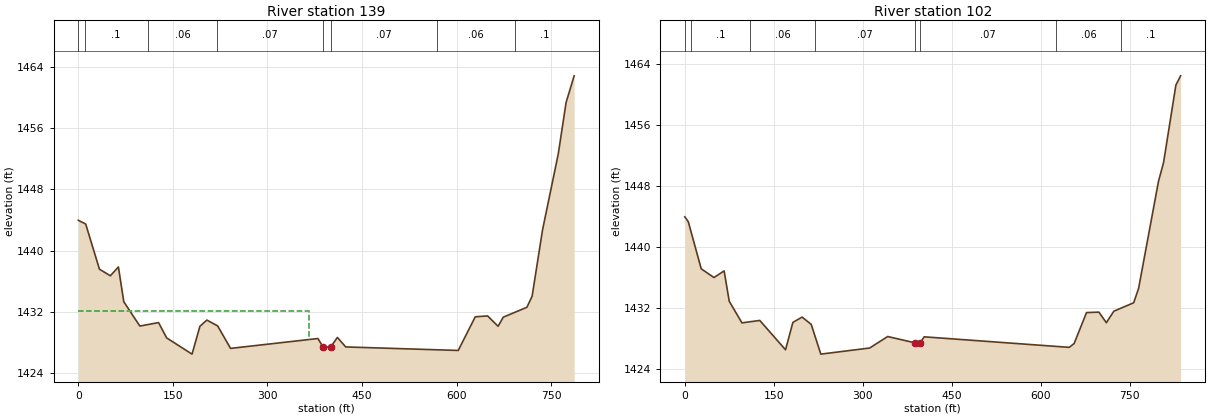
Type RM Length L Ch R = 1 ,139     ,35.8,36.3,36.7
XS GIS Cut Line= 6
2171887.96575674 695468.319545042171660.83028625 695386.38483194
2171639.05017264695400.9049076792171541.55823553695453.799469301
2171338.27717518695548.1799616052171289.53120663695725.532315276
#Sta/Elev= 30
       0 1443.96    11.7 1443.47    33.5 1437.57    50.8 1436.71    63.6 1437.86
    72.1 1433.32    97.6 1430.14   127.3 1430.59   140.1 1428.59   180.4 1426.47
   192.9 1430.11   203.9 1430.92     221 1430.16   241.5 1427.22   380.1 1428.51
   388.2 1427.41   400.2 1427.38     411 1428.65   424.2 1427.41   602.7 1426.95
   629.7 1431.35   649.3 1431.46   665.9 1430.11   674.2  1431.3   711.6 1432.59
   719.9 1434.03   736.5 1442.73   761.4 1452.63   773.8 1459.35   786.6 1462.84
#Mann= 8 ,-1,0
       0     .06       0      10      .1       0     110     .06       0
     220     .07       0   388.2    .045       0   400.2     .07       0
  568.55     .06       0  692.68      .1       0
#XS Ineff= 2 , 0
          365.52 1432.13
Permanent Ineff=
       F       F
Bank Sta=388.2,400.2
XS Rating Curve= 0 ,0
Exp/Cntr(USF)=0,0
Exp/Cntr=0.3,0.1

Type RM Length L Ch R = 1 ,102     ,,,
XS GIS Cut Line= 4
2171890.04005327695458.9852106362171656.68169318  695368.7533114
2171338.27717518 695503.582586122171267.75109302695732.792353145
#Sta/Elev= 30
       0    1444     5.9 1443.36    27.7 1437.18    49.2 1436.04    66.3 1436.91
    74.9 1432.93    96.3 1430.09   126.4 1430.41   169.8 1426.56   182.2 1430.15
   197.7 1430.85   213.1 1429.89   229.3 1425.99   311.6 1426.79     342  1428.3
   387.71427.477     397 1427.51   403.5 1428.26   647.9 1426.88   656.2 1427.37
   677.2 1431.44   698.1  1431.5   710.6 1430.11   723.2 1431.62   756.7 1432.73
     765 1434.62   798.5 1448.66     807  1451.1   827.8 1461.28   835.8  1462.5
#Mann= 8 ,-1,0
       0     .06       0      10      .1       0     110     .06       0
     220     .07       0   387.7    .045       0     397     .07       0
  625.97     .06       0  735.97      .1       0
Bank Sta=387.7,397
XS Rating Curve= 0 ,0
Exp/Cntr(USF)=0,0
Exp/Cntr=0.3,0.1
LCMann Table=0

Chan Stop Cuts=-1
Use User Specified Reach Order=0
Composite Channel Slope=5